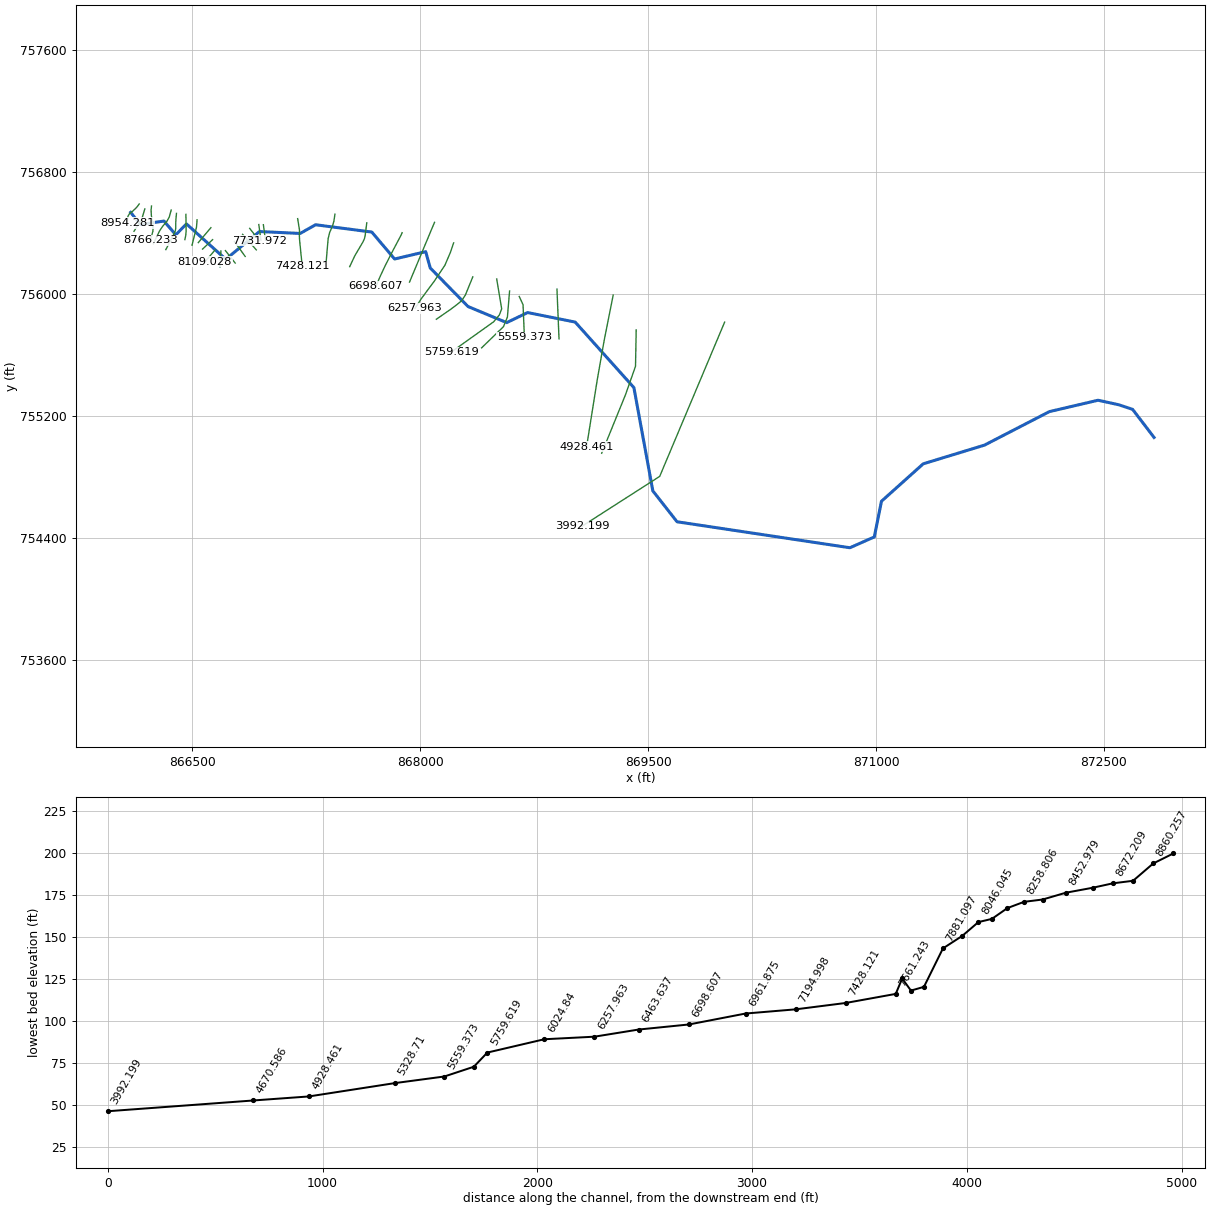
--- 9117_ras.prj (project) ---

Proj Title=9117
Current Plan=p01
Default Exp/Contr=0.3,0.1
English Units
Geom File=g01
Flow File=f01
Plan File=p01
Y Axis Title=Elevation
X Axis Title(PF)=Main Channel Distance
X Axis Title(XS)=Station
BEGIN DESCRIPTION:
RFD model 9117 exported to HEC-RAS
END DESCRIPTION:

--- 9117_ras.p01 (plan) ---

Plan Title=Plan 01
Program Version=4.10
Short Identifier=Plan 01
Geom File=g01
Flow File=f01
Subcritical Flow
Calc Critical at every XS
Secant Critical Depth

--- 9117_ras.f01 (steady flow) ---

Flow Title=Flow 01
Program Version=5.01
Number of Profiles= 6
Profile Names=10yr,25yr,50yr,100yr,100plus,500yr
River Rch & RM=9117,31,8954.281
  201.34  314.45   417.9  509.37  743.68  1229.8
River Rch & RM=9117,31,8860.257
  206.56  322.65  428.85  522.75  763.21 1257.64
River Rch & RM=9117,31,8672.209
  211.31  330.12  438.82  534.94  781.01 1282.94
River Rch & RM=9117,31,8578.185
  214.32  334.85  445.15  542.67   792.3 1298.94
River Rch & RM=9117,31,8452.979
  216.04  337.55  448.75  547.08  798.73 1308.05
River Rch & RM=9117,31,8258.806
  217.32  339.57  451.45  550.38  803.55 1314.87
River Rch & RM=9117,31,8046.045
  222.84  348.26  463.07   564.6  824.31 1344.24
River Rch & RM=9117,31,7881.097
  225.81  352.93  469.32  572.23  835.46 1359.95
River Rch & RM=9117,31,7731.972
  229.21  358.27  476.45  580.96   848.2 1377.82
River Rch & RM=9117,31,7428.121
  235.55  368.24  489.77  597.23  871.96 1411.09
River Rch & RM=9117,31,7194.998
  240.58  376.16  500.35  610.18  890.86 1437.48
River Rch & RM=9117,31,6961.875
  278.53  435.86  580.15  707.77 1033.35 1633.95
River Rch & RM=9117,31,6698.607
  284.08  444.64  591.94  722.25 1054.48 1663.02
River Rch & RM=9117,31,6463.637
     296  463.46  617.17  753.18 1099.64 1724.65
River Rch & RM=9117,31,6257.963
  298.33  467.17  622.16   759.3 1108.57 1736.88
River Rch & RM=9117,31, 6024.84
  303.77   475.8  633.75  773.54 1129.37 1765.27
River Rch & RM=9117,31,5759.619
  308.42  483.16  643.65  785.71 1147.13 1789.46
River Rch & RM=9117,31,5696.669
  309.58     485  646.12  788.74 1151.56 1795.49
River Rch & RM=9117,31,5559.373
  312.28  489.29  651.88  795.82 1161.89 1809.52
River Rch & RM=9117,31, 5328.71
  314.97  493.56  657.63  802.88  1172.2 1823.52
River Rch & RM=9117,31,4928.461
  315.74  494.78  659.27  804.89 1175.14 1827.51
Boundary for River Rch & Prof#=9117,31,1
Up Type= 0
Dn Type= 2
Boundary for River Rch & Prof#=9117,31,2
Up Type= 0
Dn Type= 2
Boundary for River Rch & Prof#=9117,31,2
Up Type= 0
Dn Type= 2
Boundary for River Rch & Prof#=9117,31,2
Up Type= 0
Dn Type= 2
Boundary for River Rch & Prof#=9117,31,2
Up Type= 0
Dn Type= 2
Boundary for River Rch & Prof#=9117,31,2
Up Type= 0
Dn Type= 2

--- 9117_ras.g01 (geometry) ---

Geom Title=9117
Program Version=4.10

River Reach=9117,31
Reach XY= 30
866092.955405609 756532.69145179866157.538738955756452.830340702
866312.399850063756475.747007366866390.177627826756385.469229664
866460.316516721756456.997007393866719.344294507 756225.05256299
866940.872072274756406.997007447867208.927627834756394.497007433
867310.316516726756451.441451796867680.455405599756403.524785189
867830.625660727756226.877695632868035.316516711756275.052562949
 868065.17762784756168.108118529868313.788738943755915.330340716
868568.649850063755809.774785226868706.149850058755875.747007371
869019.344294489755813.247007435869405.732892876755383.679156326
869530.536543637754706.327857115869689.788728382754503.968693145
870827.547419527754333.707800277870988.303035391754404.557813074
871035.383086256754638.519216128871310.220564945754883.914602876
871713.704103559755006.590468055872140.787436871755226.208523555
872461.099936919755300.861301319872596.155206077755271.438448902
872688.327786427755241.248008847872829.820143242755056.751324798

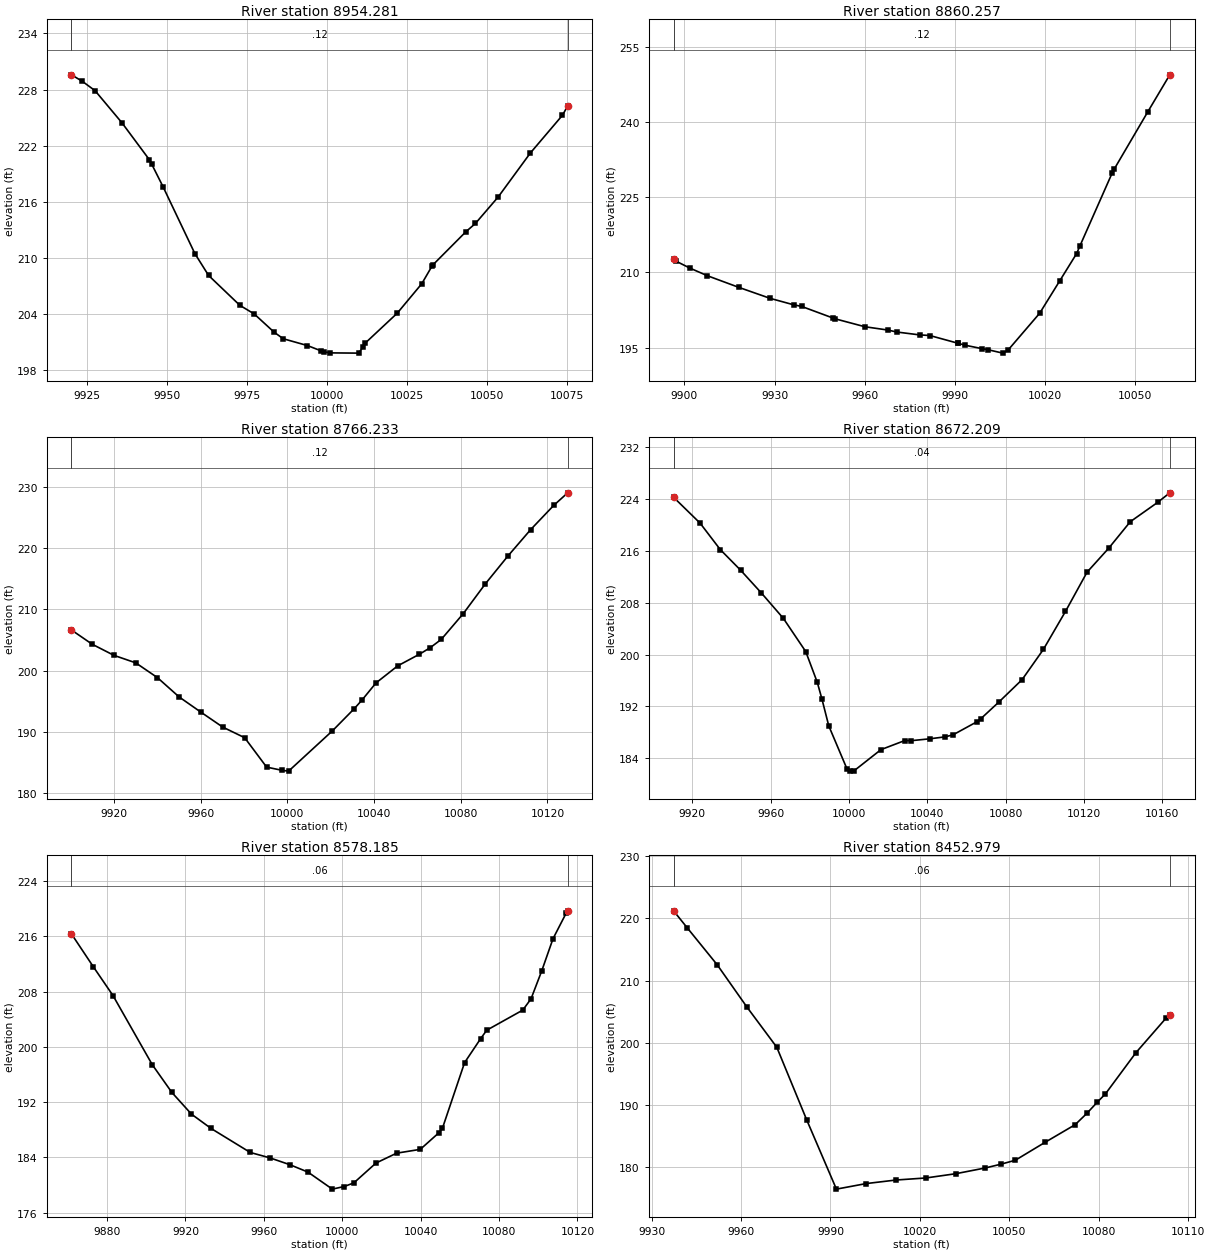
Type RM Length L Ch R = 1 ,8954.281,94.023800,94.023800,94.023800
XS GIS Cut Line= 6
866149.342046759756587.735287046866134.610772791756567.512483642
866107.398727948 756540.62806928866085.467693839756524.131044451
866075.615322756756508.512188137 866069.98702848756463.375260052
#Sta/Elev= 30
9920.141229.58389923.525228.89199927.515 227.8879935.897224.46139944.499220.4992
 9945.16220.06599948.735217.6292 9958.67 210.4899962.964208.14859972.728204.9565
9977.192 204.0439983.413202.09239986.264201.38989993.828200.66019998.148200.0879
    9999199.9857   10001199.878810009.86199.852610011.07200.470610011.94200.9449
10021.86204.118210029.53207.2673 10032.7209.136310033.11209.316310043.31212.8221
10046.27213.701610053.39216.536210063.42221.225210073.46225.265110075.09226.2587
#Mann= 3 , 0 , 0
9920.141    0.12       09920.141    0.12       010075.09    0.12       0
#XS Ineff= 2 , 0
       0                               0
Bank Sta=9920.141,10075.09
Exp/Cntr=0.3,0.1

Type RM Length L Ch R = 1 ,8860.257,94.023800,94.023800,94.023800
XS GIS Cut Line= 6
866186.547261789756555.747239509866171.094466783756504.421485646
866161.323594112756477.950395254866155.015789531756466.852229295
 866131.12988027756434.168776952866115.115605275756408.828909469
#Sta/Elev= 30
9896.402212.63849897.182212.27149901.769210.89249907.626209.35359918.069207.0319
9928.513204.82659936.456203.52149938.956203.22379949.399200.89849950.003200.7582
9960.046 199.1519967.603198.49789970.706 198.092 9978.22197.52449981.614197.4006
9990.986195.85459991.012  195.859993.328195.4641    9999194.7718   10001194.5567
10005.91193.877610007.56 194.41610018.18201.855910024.81208.290610030.46213.7752
10031.48215.197610042.32229.928410042.95230.644810054.15242.130410061.45249.5111
#Mann= 3 , 0 , 0
9896.402    0.12       09896.402    0.12       010061.45    0.12       0
#XS Ineff= 2 , 0
       0                               0
Bank Sta=9896.402,10061.45
Exp/Cntr=0.3,0.1

Type RM Length L Ch R = 1 ,8766.233,94.023700,94.023700,94.023700
XS GIS Cut Line= 6
866230.327387342756574.506854903866227.608265291756547.770395552
866229.324454782756512.893806582866240.278635472756441.408761416
866239.751845056 756410.01005233866222.933728378756349.032271825
#Sta/Elev= 26
9900.368206.63959909.924204.30989919.975202.48979930.016201.26649940.028198.8477
 9950.04195.68799960.052 193.2089970.158190.75669980.288189.01669990.418184.2058
9997.668183.675910000.55183.552310020.76190.139410030.86193.773510034.48195.2069
10040.89197.983210050.89200.7715 10060.9202.671410065.89 203.74510070.99205.0992
10081.17209.327110091.36214.201910101.77218.750910112.22223.052910122.86227.0106
10129.32229.0771
#Mann= 3 , 0 , 0
9900.368    0.12       09900.368    0.12       010129.32    0.12       0
#XS Ineff= 2 , 0
       0                               0
Bank Sta=9900.368,10129.32
Exp/Cntr=0.3,0.1

Type RM Length L Ch R = 1 ,8672.209,94.023800,94.023800,94.023800
XS GIS Cut Line= 6
866359.992030813756548.235948843866347.167063318756501.694134073
866333.855222074756477.777393228866301.190920531756437.770396762
866283.171018605756410.396763701866242.372597154756326.697889884
#Sta/Elev= 30
9910.443224.20519923.989220.21969934.274216.15599944.689 212.9729955.298209.4591
9966.466205.57189977.911200.45129983.823195.69559986.177193.14089989.668189.0099
    9999182.357810000.69182.063310002.36182.044810016.29185.351410028.42186.7476
10031.89186.736610041.15187.018210049.09 187.32210053.12187.6359 10065.1189.6112
10067.28190.109110076.69192.737210088.36196.132210099.22200.782110110.48206.6226
10121.52 212.67710132.54216.355110143.57 220.441 10157.5223.408810163.74224.8903
#Mann= 3 , 0 , 0
9910.443    0.04       09910.443    0.04       010163.74    0.04       0
#XS Ineff= 2 , 0
       0                               0
Bank Sta=9910.443,10163.74
Exp/Cntr=0.3,0.1

Type RM Length L Ch R = 1 ,8578.185,125.206800,125.206800,125.206800
XS GIS Cut Line= 6
866394.691054507756526.032523525866390.175359397756473.789080002
866389.748101388 756425.83941196866386.818010781756410.103478415
866375.243331991756385.121276427866324.677066092756288.268327798
#Sta/Elev= 28
9861.822216.33299872.937211.59949883.002207.41949903.045197.41739913.066193.3937
9923.069190.2547 9933.07188.1843 9953.07  184.719963.085183.93079973.257182.9443
 9982.51181.87119994.928179.4074   10001179.785310005.91 180.30910017.22 183.181
10027.75184.610510039.82185.1613 10049.2 187.53210051.12188.208110062.43197.7114
10070.66201.196710073.73202.401410092.11205.310510096.34 206.94210101.82211.0014
10107.55215.6391 10114.3219.363810115.04219.6776
#Mann= 3 , 0 , 0
9861.822    0.06       09861.822    0.06       010115.04    0.06       0
#XS Ineff= 2 , 0
       0                               0
Bank Sta=9861.822,10115.04
Exp/Cntr=0.3,0.1

Type RM Length L Ch R = 1 ,8452.979,107.657600,107.657600,107.657600
XS GIS Cut Line= 4
866456.880067835756519.615950148866458.216758545756409.798366616
866455.738758755 756381.12927968866449.986314123756353.885629987
#Sta/Elev= 22
9937.376221.23069941.993218.47259951.993212.55689961.994205.73549971.995 199.281
9981.996187.62949991.996176.4457   10002177.3406   10012177.9117   10022178.2409
   10032178.9232   10042 179.859 10047.2  180.4610052.02181.095510062.06183.9983
10072.09  186.8210075.98188.623810079.55190.460210082.24191.775510092.46 198.401
10102.68204.027110103.82204.5207
#Mann= 3 , 0 , 0
9937.376    0.06       09937.376    0.06       010103.82    0.06       0
#XS Ineff= 2 , 0
       0                               0
Bank Sta=9937.376,10103.82
Exp/Cntr=0.3,0.1

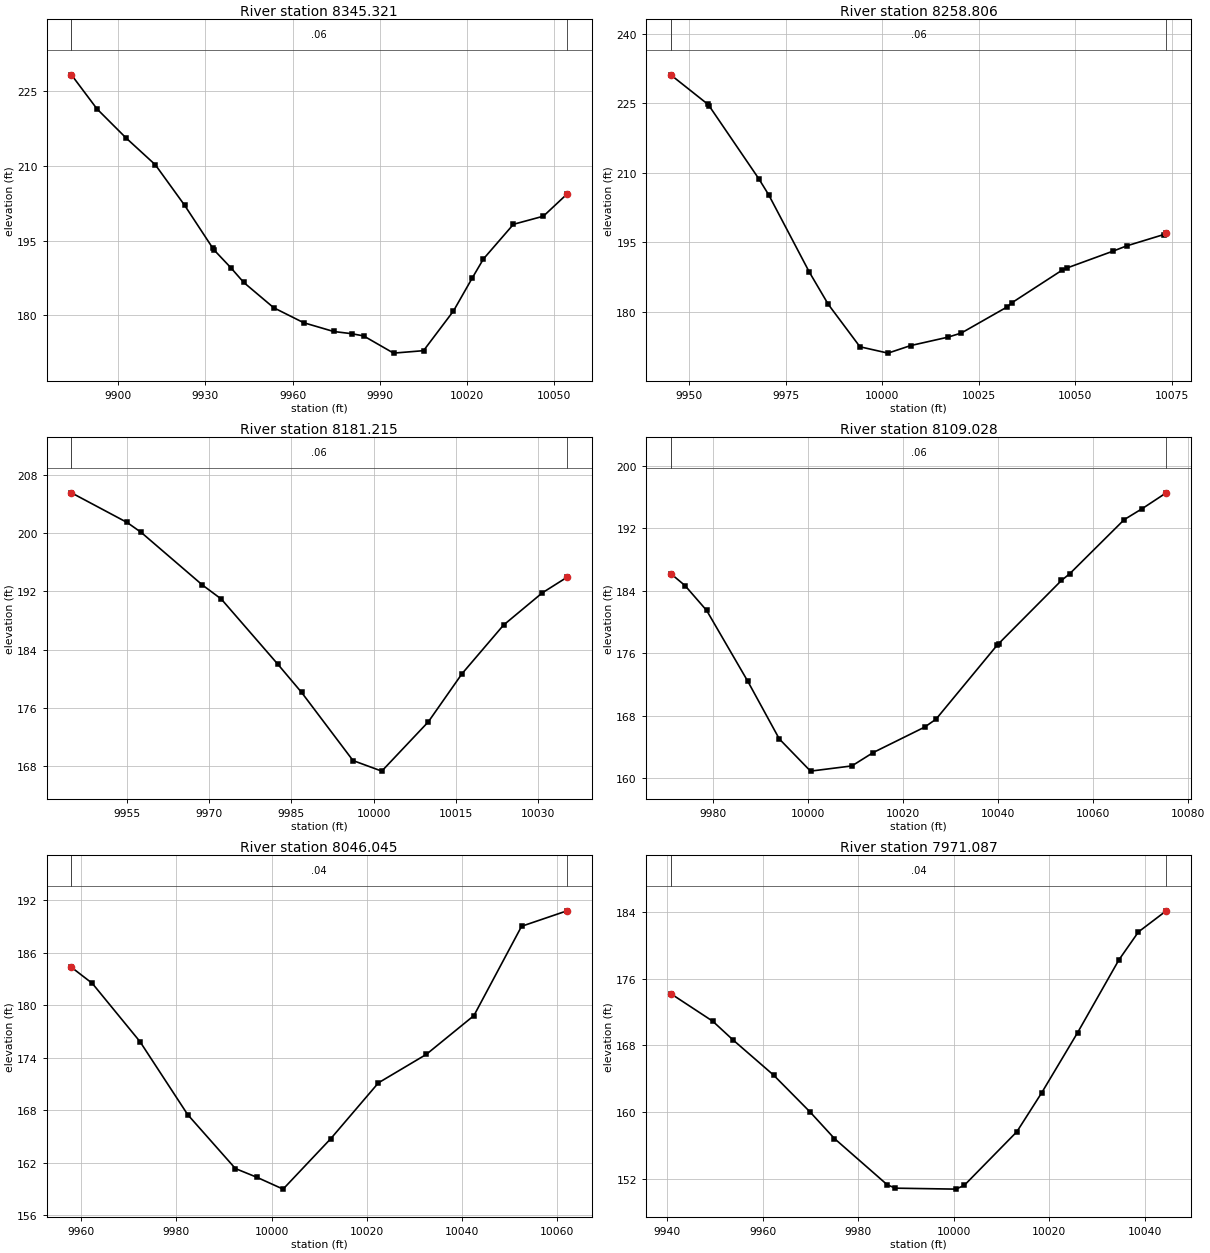
Type RM Length L Ch R = 1 ,8345.321,86.515500,86.515500,86.515500
XS GIS Cut Line= 3
866530.452843138756483.764638611866526.486364225756435.351811396
866497.165590864 756317.12657147
#Sta/Elev= 22
9883.939228.24559892.733221.39999902.767215.5517  9912.8210.18749922.834202.0888
9932.514193.48939932.877  193.179938.689189.5778 9943.18186.59249953.482181.5198
9963.785178.51349974.088176.75379980.232176.31499984.391 175.8679994.694172.4123
   10005172.9052 10015.3180.873710021.77187.5046 10025.6191.311410035.91198.2555
10046.21199.884310054.32204.3175
#Mann= 3 , 0 , 0
9883.939    0.06       09883.939    0.06       010054.32    0.06       0
#XS Ineff= 2 , 0
       0                               0
Bank Sta=9883.939,10054.32
Exp/Cntr=0.3,0.1

Type RM Length L Ch R = 1 ,8258.806,77.590600,77.590600,77.590600
XS GIS Cut Line= 2
866621.409000115756432.384573448866538.374663031756334.489945169
#Sta/Elev= 20
9945.163231.14949954.847224.74699955.071224.50519967.959208.72859970.531205.2524
9981.072188.5346 9985.99181.55469994.185172.403210001.45171.0329 10007.3172.6601
10016.91174.467610020.41175.360910032.37181.038310033.52181.903210046.64189.0014
10047.83189.430710059.75193.064610063.29194.203310072.86196.639510073.53 196.915
#Mann= 3 , 0 , 0
9945.163    0.06       09945.163    0.06       010073.53    0.06       0
#XS Ineff= 2 , 0
       0                               0
Bank Sta=9945.163,10073.53
Exp/Cntr=0.3,0.1

Type RM Length L Ch R = 1 ,8181.215,72.186600,72.186600,72.186600
XS GIS Cut Line= 2
 866632.39881818756353.668803407866566.576727251756291.925792018
#Sta/Elev= 14
9944.973205.52719955.117201.45349957.644200.11219968.828192.86859972.261190.9419
9982.539182.00979986.877178.1313 9996.25168.765710001.49167.313610009.96174.0736
10016.11180.694910023.67  187.3710030.73191.795810035.22193.9305
#Mann= 3 , 0 , 0
9944.973    0.06       09944.973    0.06       010035.22    0.06       0
#XS Ineff= 2 , 0
       0                               0
Bank Sta=9944.973,10035.22
Exp/Cntr=0.3,0.1

Type RM Length L Ch R = 1 ,8109.028,62.983400,62.983400,62.983400
XS GIS Cut Line= 2
 866649.95050651756287.279703558866581.709401818756208.301527147
#Sta/Elev= 17
9970.991186.18459974.004184.64689978.563 181.459 9987.22172.39759993.859165.0138
10000.44160.887910009.15161.554810013.65163.269310024.45166.514310026.87167.5374
10039.74177.010310040.08177.2185 10053.3185.306610055.04186.162810066.52193.0939
10070.33194.508310075.37196.5248
#Mann= 3 , 0 , 0
9970.991    0.06       09970.991    0.06       010075.37    0.06       0
#XS Ineff= 2 , 0
       0                               0
Bank Sta=9970.991,10075.37
Exp/Cntr=0.3,0.1

Type RM Length L Ch R = 1 ,8046.045,74.958200,74.958200,74.958200
XS GIS Cut Line= 2
866687.281663879756279.363992568866681.187979099756175.489159704
#Sta/Elev= 13
9957.968184.31869962.339182.48739972.356175.82899982.374167.48579992.391161.3216
9996.928160.316610002.41158.968110012.43164.740910022.44171.120310032.46174.3583
10042.48178.798710052.49 189.00810062.02190.7735
#Mann= 3 , 0 , 0
9957.968    0.04       09957.968    0.04       010062.02    0.04       0
#XS Ineff= 2 , 0
       0                               0
Bank Sta=9957.968,10062.02
Exp/Cntr=0.3,0.1

Type RM Length L Ch R = 1 ,7971.087,89.990000,89.990000,89.990000
XS GIS Cut Line= 2
866716.985100263756281.923349859866781.135632203756200.430256471
#Sta/Elev= 16
9940.743 174.2069949.554170.89269953.701168.69989962.281164.43799969.868160.0494
9975.007156.84129986.035151.31189987.734150.891410000.46150.7765 10002.2151.2384
10013.19 157.65310018.37162.303110025.91169.536110034.54  178.2410038.64181.6022
10044.46184.1284
#Mann= 3 , 0 , 0
9940.743    0.04       09940.743    0.04       010044.46    0.04       0
#XS Ineff= 2 , 0
       0                               0
Bank Sta=9940.743,10044.46
Exp/Cntr=0.3,0.1

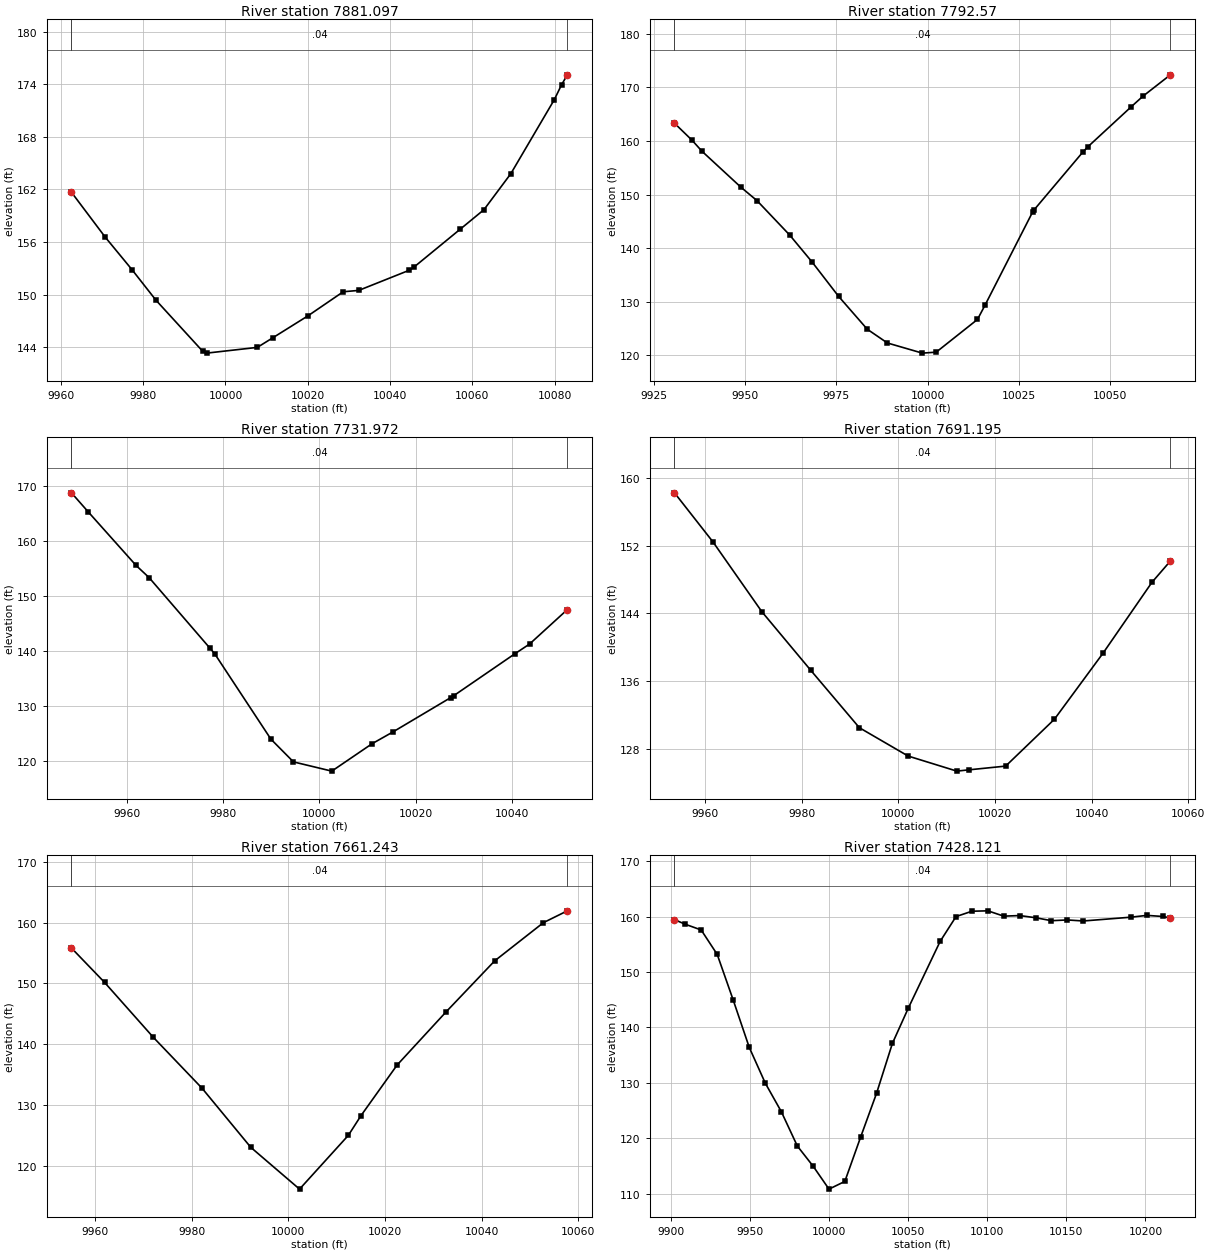
Type RM Length L Ch R = 1 ,7881.097,88.526700,88.526700,88.526700
XS GIS Cut Line= 2
866776.376141305  756341.6559127866846.853225015756243.859216717
#Sta/Elev= 19
9962.559161.67059970.763156.55199977.309152.81969983.089149.36089994.414143.5518
9995.415143.316410007.74143.971310011.52145.071610020.07147.578410028.62150.3191
10032.39150.473210044.72152.781610045.73153.097410057.05157.453710062.83159.6842
10069.37163.797410079.93172.2376 10081.7173.9409 10083.1  175.07
#Mann= 3 , 0 , 0
9962.559    0.04       09962.559    0.04       0 10083.1    0.04       0
#XS Ineff= 2 , 0
       0                               0
Bank Sta=9962.559,10083.1
Exp/Cntr=0.3,0.1

Type RM Length L Ch R = 1 , 7792.57,60.598400,60.598400,60.598400
XS GIS Cut Line= 2
 866830.03209035756388.613268973866919.999575213756287.025720227
#Sta/Elev= 21
9930.716163.31929935.542160.12889938.209158.1083  9948.9151.37539953.292148.8769
9962.258142.44069968.375137.42089975.616131.02369983.458124.89069988.973 122.321
9998.541120.427310002.33120.607510013.62126.709710015.69129.368910028.71146.7498
10029.05147.1029 10042.4157.888910043.79158.895310055.76166.427410058.87168.3377
10066.41172.3464
#Mann= 3 , 0 , 0
9930.716    0.04       09930.716    0.04       010066.41    0.04       0
#XS Ineff= 2 , 0
       0                               0
Bank Sta=9930.716,10066.41
Exp/Cntr=0.3,0.1

Type RM Length L Ch R = 1 ,7731.972,40.776900,40.776900,40.776900
XS GIS Cut Line= 2
866876.798326586756427.744374822866939.793196158756346.329829695
#Sta/Elev= 16
9948.556168.78669952.026165.33469961.959155.5957 9964.67153.37869977.314140.5382
  9978.3139.52139989.958124.01419994.641119.8793 10002.6 118.20110010.98123.1916
10015.25125.301510027.32131.581410027.89131.897610040.53139.486610043.66141.3036
 10051.5147.5647
#Mann= 3 , 0 , 0
9948.556    0.04       09948.556    0.04       0 10051.5    0.04       0
#XS Ineff= 2 , 0
       0                               0
Bank Sta=9948.556,10051.5
Exp/Cntr=0.3,0.1

Type RM Length L Ch R = 1 ,7691.195,29.951300,29.951300,29.951300
XS GIS Cut Line= 2
866936.633797969756452.908189702866950.742365304756351.221487725
#Sta/Elev= 13
9953.649158.21239961.633152.41149971.729144.20259981.825137.3128 9991.92 130.522
10002.02 127.17910012.11125.401910014.53125.550610022.21125.9939 10032.3131.5171
 10042.4139.3322 10052.5147.665310056.31150.1725
#Mann= 3 , 0 , 0
9953.649    0.04       09953.649    0.04       010056.31    0.04       0
#XS Ineff= 2 , 0
       0                               0
Bank Sta=9953.649,10056.31
Exp/Cntr=0.3,0.1

Type RM Length L Ch R = 1 ,7661.243,233.122700,233.122700,233.122700
XS GIS Cut Line= 2
866966.762041249756451.777561982866980.870657032 756350.09086476
#Sta/Elev= 13
9955.079155.80929961.921150.17719972.017141.15999982.113132.79579992.209123.0882
 10002.3116.2302 10012.4125.058310015.02128.2954 10022.5136.607910032.59145.2918
10042.69153.699110052.78159.974110057.74161.9184
#Mann= 3 , 0 , 0
9955.079    0.04       09955.079    0.04       010057.74    0.04       0
#XS Ineff= 2 , 0
       0                               0
Bank Sta=9955.079,10057.74
Exp/Cntr=0.3,0.1

Type RM Length L Ch R = 1 ,7428.121,233.122800,233.122800,233.122800
XS GIS Cut Line= 6
867192.455776138 756491.64728477867204.410852142756416.824321896
 867204.56044602756396.068805049 867203.66379107756380.083905914
867204.933308291 756354.12647088867222.377791572756180.262848574
#Sta/Elev= 30
9902.472159.44779909.204158.6227 9919.33157.58549929.457153.17549939.584144.9264
9949.711 136.3949959.838129.94369969.965124.79799980.068118.60739990.069114.9603
10000.08110.824710010.09112.215810020.11120.250710030.12128.110910040.13137.1187
10050.18 143.48210070.28155.517110080.33159.998710090.38160.965710100.43161.0373
10110.48160.078310120.53160.182810130.58159.793110140.63159.257610150.68159.3908
10160.73159.204610190.88159.892110200.93160.215310210.98160.016110215.74159.7467
#Mann= 3 , 0 , 0
9902.472    0.04       09902.472    0.04       010215.74    0.04       0
#XS Ineff= 2 , 0
       0                               0
Bank Sta=9902.472,10215.74
Exp/Cntr=0.3,0.1

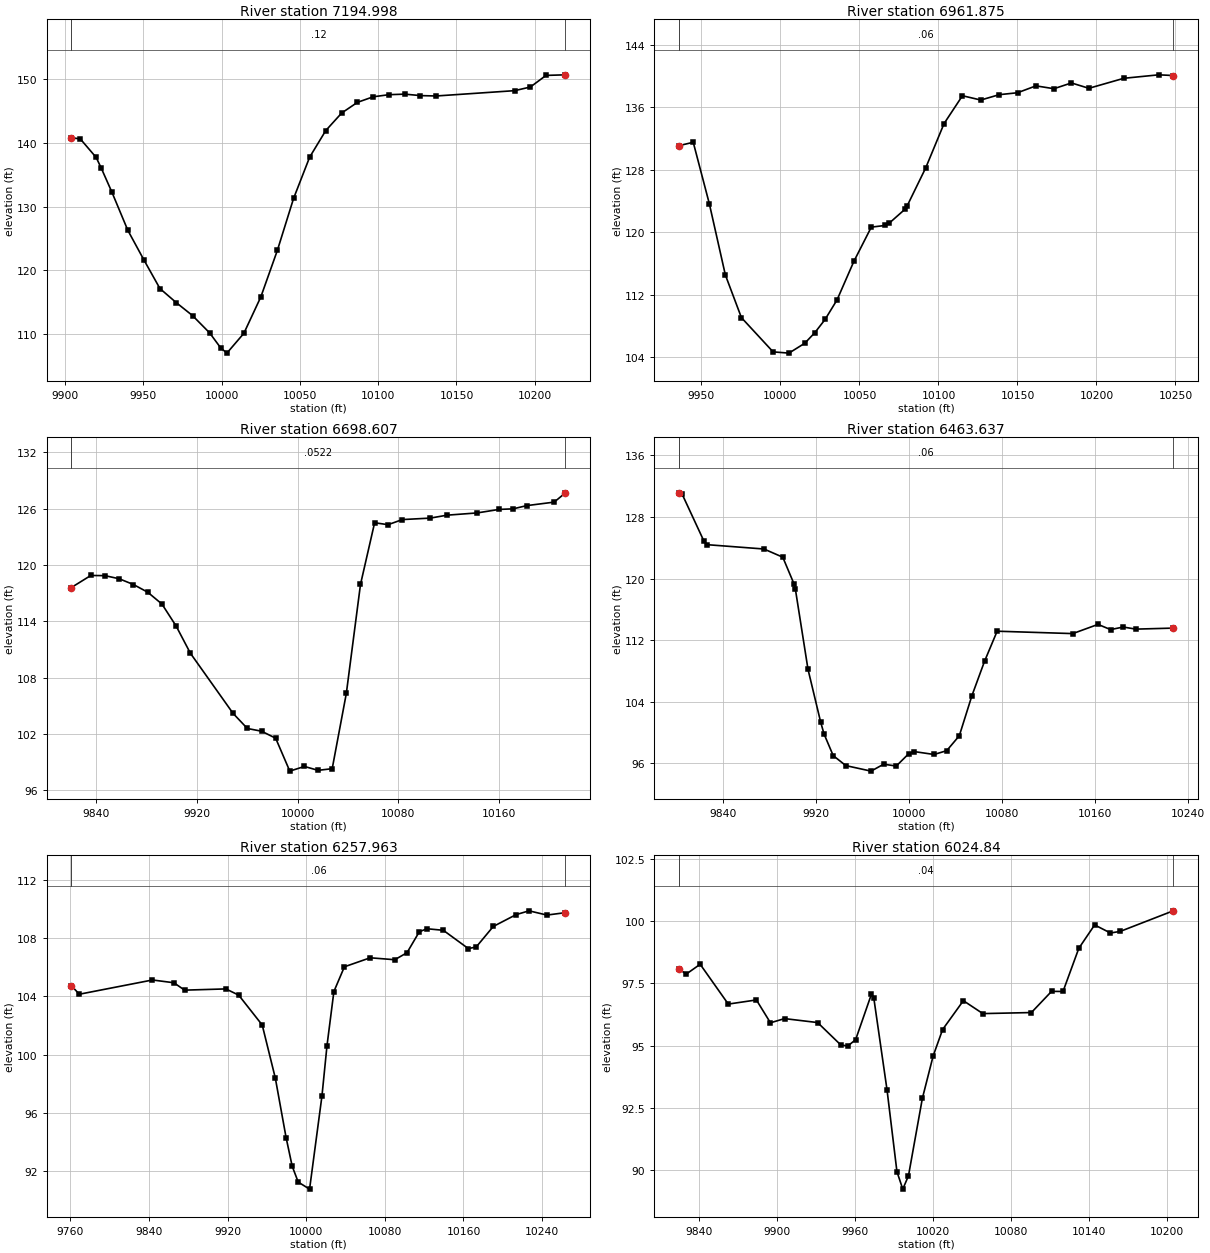
Type RM Length L Ch R = 1 ,7194.998,233.122700,233.122700,233.122700
XS GIS Cut Line= 6
867437.918315372756520.651994659867430.890023679756475.057290618
867422.841810046756446.221145329 867402.47000518756399.132886772
867392.972622418756358.932870911867380.400778316756212.643250942
#Sta/Elev= 30
9904.033140.80019909.751140.60759919.869137.70769923.188135.99799929.988132.2261
9940.106126.27799950.225121.70569960.607117.1547 9970.99114.95959981.441112.9138
9992.385110.19699999.362107.870310003.35 107.037 10014.2110.142310025.05115.8565
10035.66123.187210045.94131.277210056.21137.747710066.49141.912310076.68144.6722
10086.75146.343110096.82147.213510106.89147.541210116.96147.628410126.99147.3995
10137.01147.339410187.14148.173510197.17148.744510207.19150.565210219.58150.6548
#Mann= 3 , 0 , 0
9904.033    0.12       09904.033    0.12       010219.58    0.12       0
#XS Ineff= 2 , 0
       0                               0
Bank Sta=9904.033,10219.58
Exp/Cntr=0.3,0.1

Type RM Length L Ch R = 1 ,6961.875,263.268000,263.268000,263.268000
XS GIS Cut Line= 6
 867647.32956107756463.673881402867636.565662439756378.634635686
867631.775146459756359.526532303867621.382552924756337.102966944
867569.083846497756249.042554934867535.056695331756176.695027614
#Sta/Elev= 30
  9935.9131.09169944.811131.51589954.972123.67559965.133114.54789975.294109.0868
9995.345104.705210005.37104.5434 10015.4105.809310021.79107.167910028.23108.8459
10035.84111.362610046.48 116.288 10057.5120.6624 10066.2120.874410068.65121.1351
 10078.7122.930210080.28123.418510091.91128.233810103.54133.907210115.17137.4698
 10126.8136.920310138.43137.605310150.06137.853610161.69138.733410173.09138.3688
10184.14139.107110195.19138.421310217.29 139.70110239.39140.144910248.57140.0574
#Mann= 3 , 0 , 0
  9935.9    0.06       0  9935.9    0.06       010248.57    0.06       0
#XS Ineff= 2 , 0
       0                               0
Bank Sta=9935.9,10248.57
Exp/Cntr=0.3,0.1

Type RM Length L Ch R = 1 ,6698.607,234.970500,234.970500,234.970500
XS GIS Cut Line= 6
867880.143442959756399.132529277867873.006421014756383.098625635
867814.662466575756273.023298008867769.549048524756185.008320565
867737.685937859756117.372091106867707.086876664756046.791080543
#Sta/Elev= 30
9820.129117.58819835.598118.87269846.845118.85179858.163118.52059869.481117.9059
9880.799117.09179892.117115.82959903.434113.47829914.752110.58749948.706104.1801
9960.024102.57859971.277102.28989982.514101.54419993.75298.0383510005.3798.53774
10016.2398.1220610027.4698.29883 10038.7106.321210049.94117.914310061.17 124.486
10071.84124.279710083.28124.824110105.39124.979810118.77125.292310142.68125.5311
10160.31125.907310171.21125.964910182.11126.309810203.91 126.68210212.86127.6713
#Mann= 3 , 0 , 0
9820.129  0.0522       09820.129  0.0522       010212.86  0.0522       0
#XS Ineff= 2 , 0
       0                               0
Bank Sta=9820.129,10212.86
Exp/Cntr=0.3,0.1

Type RM Length L Ch R = 1 ,6463.637,205.674200,205.674200,205.674200
XS GIS Cut Line= 2
 868093.25342302756467.181062444867928.667357112756075.332213999
#Sta/Elev= 30
9802.053131.13489804.419131.02689823.366 124.8659826.111124.40339875.012123.8418
9891.189122.77769900.835119.31799902.035118.62239912.882108.22779923.728101.3967
9926.65899.838189934.574 97.01959945.42195.723589967.11395.006299977.95995.90485
9988.80695.666389999.65297.2844710004.1397.5453110021.3497.1671410032.1997.66124
10043.0499.5960810053.88104.797310064.73109.259610075.58113.171110140.65112.8603
10162.35114.055210173.19113.378910184.04 113.71310194.89113.440310227.06113.5736
#Mann= 3 , 0 , 0
9802.053    0.06       09802.053    0.06       010227.06    0.06       0
#XS Ineff= 2 , 0
       09944.065                       0
Bank Sta=9802.053,10227.06
Exp/Cntr=0.3,0.1

Type RM Length L Ch R = 1 ,6257.963,233.122800,233.122800,233.122800
XS GIS Cut Line= 6
868219.151987391756332.655705788868197.901529202 756270.23929521
868161.866328286756186.444763757868091.913901729756081.653585194
868009.526351946755971.273178437867964.645838129755903.077035215
#Sta/Elev= 30
9761.133 104.735 9769.22104.14899843.656105.12829865.427104.93739876.313104.4298
9918.282104.51439931.325104.08929955.266102.03569968.61998.38143 9979.5794.29614
9985.75592.334729991.88491.2429610003.4490.7589210016.0697.1715210021.16100.6154
10028.17104.332810038.87106.033910065.12 106.65310090.08106.519710102.56107.0019
10115.04108.437410122.77108.648410139.49 108.54210164.95107.284910172.93107.3948
10190.31108.804710213.53109.618510226.69109.879310244.88109.588310263.72109.7541
#Mann= 3 , 0 , 0
9761.133    0.06       09761.133    0.06       010263.72    0.06       0
#XS Ineff= 2 , 0
       0                               0
Bank Sta=9761.133,10263.72
Exp/Cntr=0.3,0.1

Type RM Length L Ch R = 1 , 6024.84,265.221100,265.221100,265.221100
XS GIS Cut Line= 6
 868345.34534512756109.944959151 868296.22545884755990.011527062
868271.150157381755953.037850649868241.496725443755928.393769754
868200.794062263 755897.81507505868105.274894104755831.869296583
#Sta/Elev= 30
9824.72398.080059830.06797.867559840.87398.265289862.48596.666439884.09896.83287
9894.90495.91497 9905.7196.083469931.17495.924499948.93595.027659954.32594.98147
9960.38195.236079972.46497.053299974.32596.923529984.54693.212319992.14189.93666
9996.62989.23478   1000189.7683510011.6792.8760610019.96 94.580310027.2695.64548
10043.2196.8031710058.1996.2843110095.5196.3266510111.0397.1783510119.8197.17229
10131.9798.9080510144.12 99.845910156.2799.5219210163.8399.5862110204.54 100.412
#Mann= 3 , 0 , 0
9824.723    0.04       09824.723    0.04       010204.54    0.04       0
#XS Ineff= 2 , 0
       0                10035.86       0
Bank Sta=9824.723,10204.54
Exp/Cntr=0.3,0.1

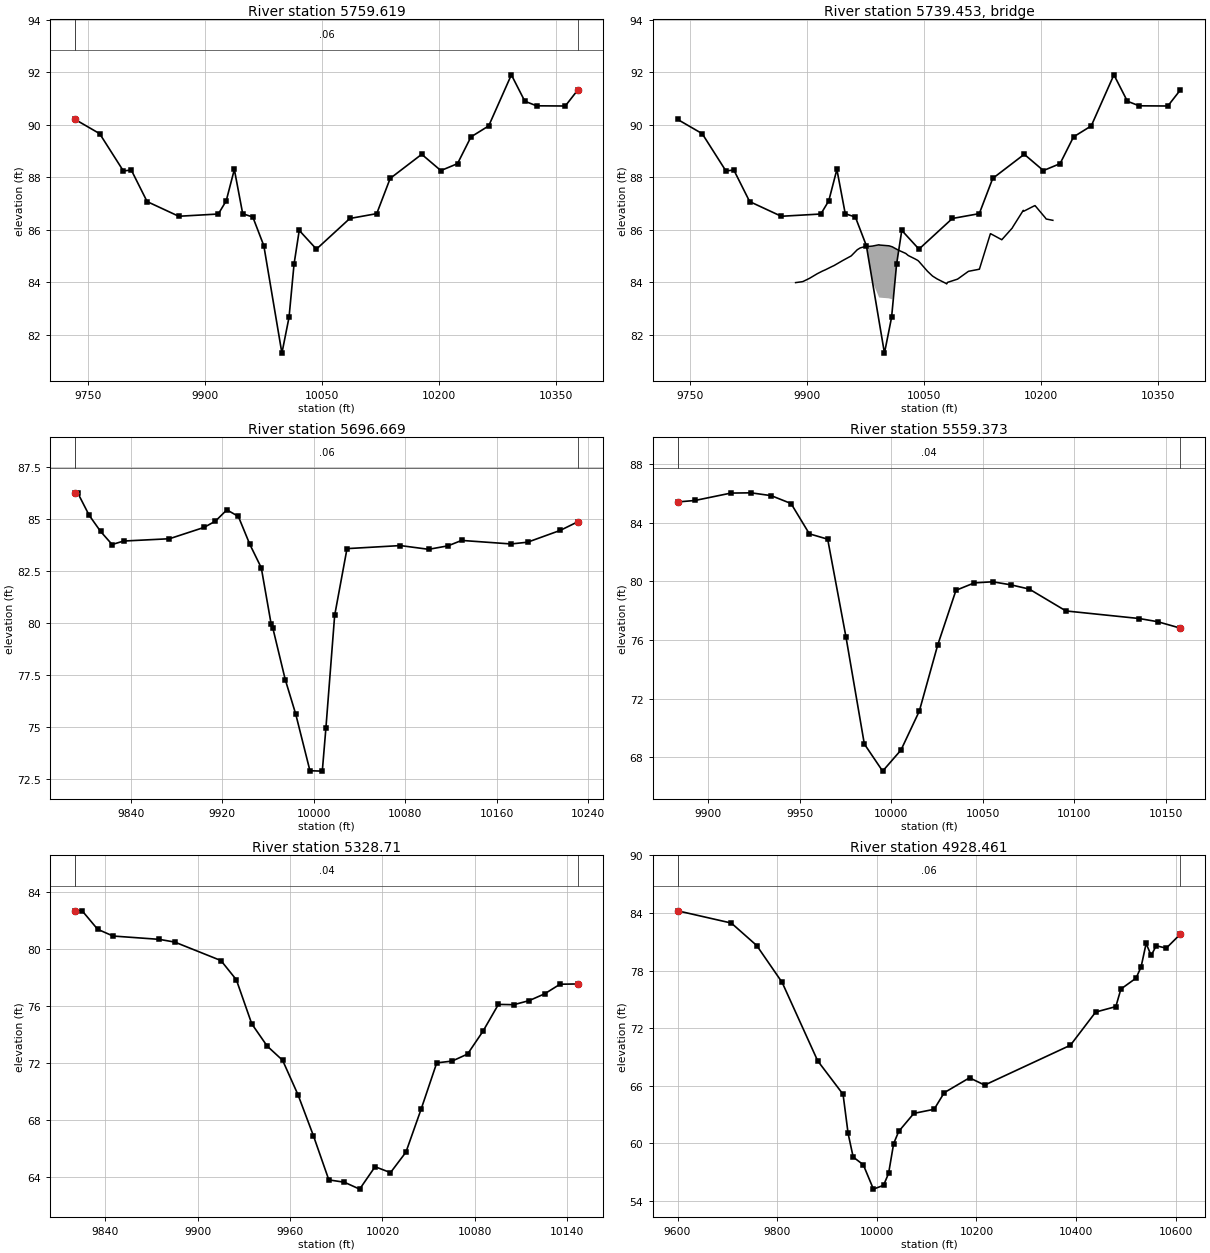
Type RM Length L Ch R = 1 ,5759.619,62.949200,62.949200,62.949200
XS GIS Cut Line= 5
868502.619710698756095.950012003868535.462156934755899.998423361
868519.915187478755859.749765645868482.252403989 755814.94606548
868201.984038922755615.703110426
#Sta/Elev= 30
9734.02290.196669765.403  89.6579795.82288.237919805.96188.27335 9826.2487.07284
9866.79886.514089917.49686.599959927.63587.100499938.06588.295639948.78586.60978
9961.74286.485299975.85385.394769999.033 81.307110008.1982.6716510014.5784.68678
10021.2585.9762710043.2885.2638110086.0786.4298910120.5986.6141110137.8487.95495
10178.2588.8719910202.78 88.252810224.14 88.5156 10241.489.5342110264.1389.95256
10293.1891.8955210310.4390.8913710325.4890.7166410362.2990.7093110378.2691.31617
#Mann= 3 , 0 , 0
9734.022    0.06       09734.022    0.06       010378.26    0.06       0
#XS Ineff= 2 , 0
       09972.262        10022.68       0
Bank Sta=9734.022,10378.26
Exp/Cntr=0.3,0.1

Type RM Length L Ch R = 3 ,5739.453,,,
BEGIN DESCRIPTION:
END DESCRIPTION:
Bridge Culvert--1,0,-1,-1, 0
Deck Dist Width WeirC Skew NumUp NumDn MinLoCord MaxHiCord MaxSubmerge Is_Ogee
19.474600,24.000000,2.6,0, 55, 55, , , 0.95, 0, 0,0,,
 9885.12 9892.60 9894.46 9902.80 9913.00 9919.62 9923.49 9931.60 9934.51 9945.52
 9955.44 9956.54 9964.15 9967.96 9975.00 9980.29 9983.57 9983.57 9992.11 9992.61
10004.9410009.2110011.5710011.5710017.2610026.3210029.5910038.3410041.9810043.35
10054.2410060.6410066.5110077.9210078.7710079.9410092.5010092.6510106.7110106.73
10120.7710120.9510134.8310135.1810148.8910149.4110162.9510163.6310177.0110177.86
10191.0710192.0910205.1310206.3110214.93
   83.99   84.02   84.03   84.15   84.33   84.43   84.48   84.60   84.64   84.83
   84.99   85.01   85.24   85.31   85.37   85.37   85.38   85.38   85.43   85.42
   85.39   85.35   85.31   85.31   85.22   85.10   85.02   84.89   84.83   84.79
   84.42   84.24   84.13   83.96   83.94   84.00   84.12   84.12   84.42   84.42
   84.50   84.52   85.85   85.85   85.63   85.62   86.07   86.11   86.74   86.71
   86.91   86.92   86.46   86.41   86.36
 -916.01 -915.98 -915.97 -915.85 -915.67 -915.57 -915.52 -915.40 -915.36 -915.17
 -915.01 -914.99 -914.76 -914.69 -914.63 -914.63 -914.62   83.38   83.43   83.42
   83.39   83.35   83.31 -914.69 -914.78 -914.90 -914.98 -915.11 -915.17 -915.21
 -915.58 -915.76 -915.87 -916.04 -916.06 -916.00 -915.88 -915.88 -915.58 -915.58
 -915.50 -915.48 -914.15 -914.15 -914.37 -914.38 -913.93 -913.89 -913.26 -913.29
 -913.09 -913.08 -913.54 -913.59 -913.64
 9885.12 9892.60 9894.46 9902.80 9913.00 9919.62 9923.49 9931.60 9934.51 9945.52
 9955.44 9956.54 9964.15 9967.96 9975.00 9980.29 9982.02 9982.02 9992.11 9992.61
10004.9410009.2110010.0210010.0210017.2610026.3210029.5910038.3410041.9810043.35
10054.2410060.6410066.5110077.9210078.7710079.9410092.5010092.6510106.7110106.73
10120.7710120.9510134.8310135.1810148.8910149.4110162.9510163.6310177.0110177.86
10191.0710192.0910205.1310206.3110214.93
   83.99   84.02   84.03   84.15   84.33   84.43   84.48   84.60   84.64   84.83
   84.99   85.01   85.24   85.31   85.37   85.37   85.38   85.38   85.43   85.42
   85.39   85.35   85.33   85.33   85.22   85.10   85.02   84.89   84.83   84.79
   84.42   84.24   84.13   83.96   83.94   84.00   84.12   84.12   84.42   84.42
   84.50   84.52   85.85   85.85   85.63   85.62   86.07   86.11   86.74   86.71
   86.91   86.92   86.46   86.41   86.36
 -916.01 -915.98 -915.97 -915.85 -915.67 -915.57 -915.52 -915.40 -915.36 -915.17
 -915.01 -914.99 -914.76 -914.69 -914.63 -914.63 -914.62   83.38   83.43   83.42
   83.39   83.35   83.33 -914.67 -914.78 -914.90 -914.98 -915.11 -915.17 -915.21
 -915.58 -915.76 -915.87 -916.04 -916.06 -916.00 -915.88 -915.88 -915.58 -915.58
 -915.50 -915.48 -914.15 -914.15 -914.37 -914.38 -913.93 -913.89 -913.26 -913.29
 -913.09 -913.08 -913.54 -913.59 -913.64
BR Coef=-1 , 0 , 0 ,, 0 ,,,0.8,0,1,0,
WSPro=,,,, 1 ,,,, 0 ,,,, 0 ,,,,-1 ,-1 ,-1 , 0 , 0 , 0 , 0 , 0
BC Design=,, 0 ,, 0 ,,,,,,

Type RM Length L Ch R = 1 ,5696.669,137.296400,137.296400,137.296400
XS GIS Cut Line= 4
868587.445519007756017.188116005868573.116128277755846.356897795
868547.405799312 755783.54974621868403.436086795755644.430973293
#Sta/Elev= 30
9791.43586.24199 9793.6386.249539803.66685.170239813.70184.391029823.73683.76345
9833.771 83.93069873.91184.042139904.01784.584449914.05284.886649924.087 85.4305
9934.12285.116659944.15783.772629954.19282.644679962.86679.923629964.33279.73764
9975.13777.270689984.28975.613959996.74872.8860310007.5572.8671710010.69 74.9297
10018.36  80.35610029.1683.5663310075.79 83.7131 10100.683.5332810117.5183.70096
10129.38  83.96110172.5583.7909410187.0483.8751510215.7284.4453410230.9384.85533
#Mann= 3 , 0 , 0
9791.435    0.06       09791.435    0.06       010230.93    0.06       0
#XS Ineff= 2 , 0
       0 9956.61        10027.19       0
Bank Sta=9791.435,10230.93
Exp/Cntr=0.3,0.1

Type RM Length L Ch R = 1 ,5559.373,230.662700,230.662700,230.662700
XS GIS Cut Line= 3
868651.014264718755981.341778968868676.118177948755927.196433976
868684.983597994755712.604626783
#Sta/Elev= 23
9883.41985.402679892.89485.505589912.45486.008089923.47686.025599934.49985.83267
9945.29985.297319955.30783.231769965.31682.867249975.32476.190469985.33368.91015
9995.34167.0616110005.3568.4981510015.3671.1527810025.3775.6416610035.3879.38384
10045.3879.8878510055.3979.96426 10065.479.7554110075.4179.4667610095.43 77.9767
10135.4677.4600710145.4777.2456910157.8876.80659
#Mann= 3 , 0 , 0
9883.419    0.04       09883.419    0.04       010157.88    0.04       0
#XS Ineff= 2 , 0
       0                               0
Bank Sta=9883.419,10157.88
Exp/Cntr=0.3,0.1

Type RM Length L Ch R = 1 , 5328.71,400.249200,400.249200,400.249200
XS GIS Cut Line= 2
868899.336518986756029.563108446 868912.80738338755703.522334437
#Sta/Elev= 30
9820.45282.708859825.01982.706419835.028 81.41179845.03680.935689875.06280.70145
 9885.0780.510919915.09679.210359925.10477.859139935.11374.756049945.12173.19266
 9955.1372.194579965.13969.767669975.14766.884979985.15663.776339995.16463.61619
10005.1763.1276110015.1864.7036910025.1964.28911 10035.265.7257110045.21 68.7937
10055.2272.0111910065.2272.1372710075.23 72.631110085.2474.2360810095.2576.12485
10105.2676.1045410115.2776.3933110125.2876.8691610135.2877.5451410146.7777.56395
#Mann= 3 , 0 , 0
9820.452    0.04       09820.452    0.04       010146.77    0.04       0
#XS Ineff= 2 , 0
       0                               0
Bank Sta=9820.452,10146.77
Exp/Cntr=0.3,0.1

Type RM Length L Ch R = 1 ,4928.461,257.874900,257.874900,257.874900
XS GIS Cut Line= 4
869269.533028951755990.494778477869209.464870918755690.048285645
869164.109251656755432.307805224869094.586522843754997.289428567
#Sta/Elev= 30
9600.36684.227399707.94882.951699758.93880.606629809.92776.758059881.31368.57382
9932.19165.085749942.34560.998769952.49958.541669972.80657.737279993.11355.19339
10013.4255.5904610023.5756.8316210033.7359.9421410043.88 61.214310074.3463.09633
10114.9663.5222310135.2665.2552610185.9966.8063510216.3766.0484210388.5270.20687
10439.1673.6653110479.6774.2358510489.7976.0659810520.1777.20464 10530.3 78.3673
10540.4380.8189810550.5579.5690110560.6880.5822110580.9480.33371   1060981.78731
#Mann= 3 , 0 , 0
9600.366    0.06       09600.366    0.06       0   10609    0.06       0
#XS Ineff= 2 , 0
       0                10139.93       0
Bank Sta=9600.366,10609
Exp/Cntr=0.3,0.1

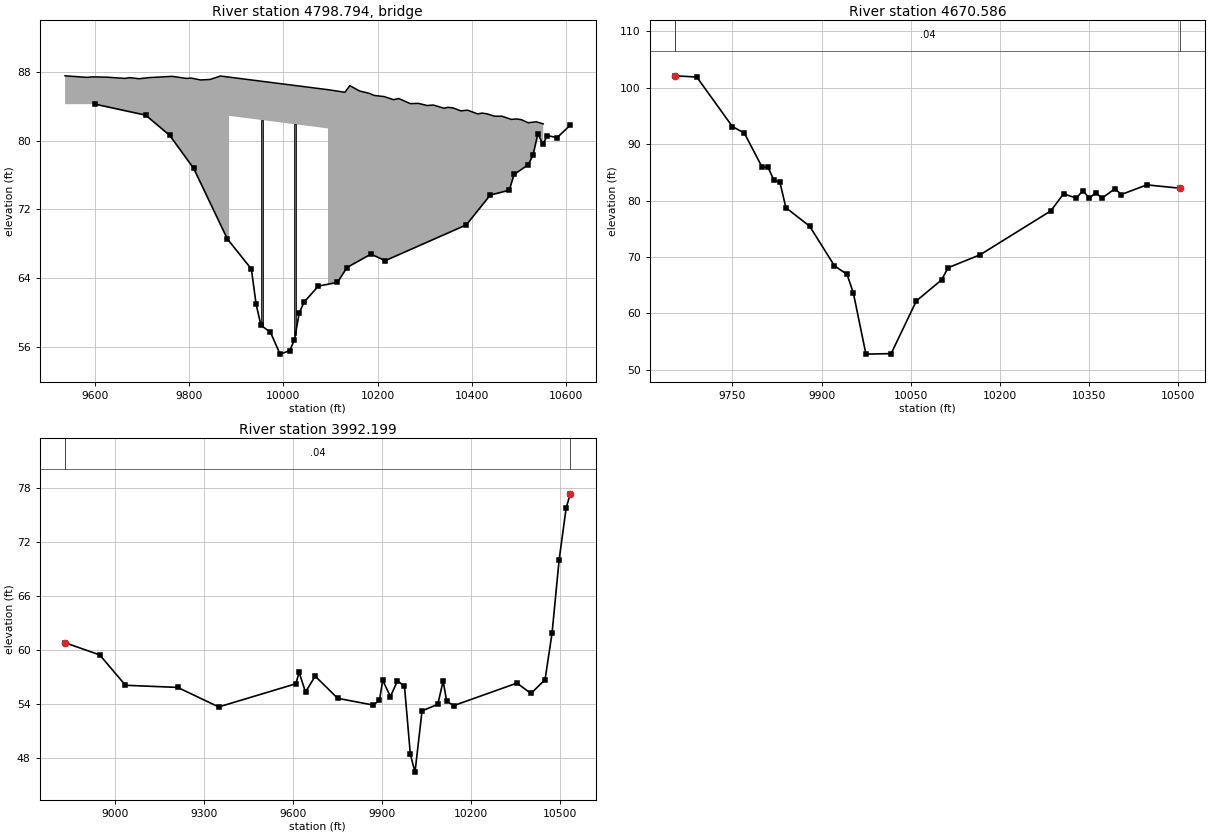
Type RM Length L Ch R = 3 ,4798.794,,,
BEGIN DESCRIPTION:
END DESCRIPTION:
Bridge Culvert--1,0,-1,-1, 0
Deck Dist Width WeirC Skew NumUp NumDn MinLoCord MaxHiCord MaxSubmerge Is_Ogee
68.937450,120.000000,2.6,0, 46, 46, , , 0.95, 0, 0,0,,
 9536.86 9583.95 9593.96 9624.00 9664.05 9674.06 9694.08 9714.11 9764.24 9794.41
 9804.47 9824.59 9844.71 9866.54 9884.92 9884.9210094.9210094.9210130.8710141.11
10161.8710182.7110193.1210213.9610233.8610245.2010269.5910286.8710305.3210318.12
10341.0510349.3710359.7810376.7810391.0310412.5110422.2810432.7010448.2410463.95
10483.9710495.1910505.6110519.7010536.8610551.64
   87.52   87.34   87.40   87.37   87.22   87.31   87.18   87.31   87.46   87.22
   87.26   87.04   87.10   87.50   87.37   87.37   85.91   85.91   85.61   86.38
   85.76   85.48   85.24   85.11   84.75   84.88   84.29   84.32   84.07   84.13
   83.76   83.86   83.80   83.45   83.53   83.10   83.19   83.10   82.83   82.83
   82.46   82.51   82.42   82.07   82.18   81.94
 -912.48 -912.66 -912.60 -912.63 -912.78 -912.69 -912.82 -912.69 -912.54 -912.78
 -912.74 -912.96 -912.90 -912.50 -912.63   82.87   81.41 -914.09 -914.39 -913.62
 -914.24 -914.52 -914.76 -914.89 -915.25 -915.12 -915.71 -915.68 -915.93 -915.87
 -916.24 -916.14 -916.20 -916.55 -916.47 -916.90 -916.81 -916.90 -917.17 -917.17
 -917.54 -917.49 -917.58 -917.93 -917.82 -918.06
 9536.86 9583.95 9593.96 9624.00 9664.05 9674.06 9694.08 9714.11 9764.24 9794.41
 9804.47 9824.59 9844.71 9866.54 9901.01 9901.0110111.0110111.0110130.8710141.11
10161.8710182.7110193.1210213.9610233.8610245.2010269.5910286.8710305.3210318.12
10341.0510349.3710359.7810376.7810391.0310412.5110422.2810432.7010448.2410463.95
10483.9710495.1910505.6110519.7010536.8610551.64
   87.52   87.34   87.40   87.37   87.22   87.31   87.18   87.31   87.46   87.22
   87.26   87.04   87.10   87.50   87.26   87.26   85.80   85.80   85.61   86.38
   85.76   85.48   85.24   85.11   84.75   84.88   84.29   84.32   84.07   84.13
   83.76   83.86   83.80   83.45   83.53   83.10   83.19   83.10   82.83   82.83
   82.46   82.51   82.42   82.07   82.18   81.94
 -912.48 -912.66 -912.60 -912.63 -912.78 -912.69 -912.82 -912.69 -912.54 -912.78
 -912.74 -912.96 -912.90 -912.50 -912.74   82.76   81.30 -914.20 -914.39 -913.62
 -914.24 -914.52 -914.76 -914.89 -915.25 -915.12 -915.71 -915.68 -915.93 -915.87
 -916.24 -916.14 -916.20 -916.55 -916.47 -916.90 -916.81 -916.90 -917.17 -917.17
 -917.54 -917.49 -917.58 -917.93 -917.82 -918.06
Pier Skew, UpSta & Num, DnSta & Num=  ,9954.26, 2 ,9970.35, 2 , 0 , 0 , 0 ,,
    4.00    4.00
 -913.11   86.89
    4.00    4.00
 -913.22   86.78
Pier Skew, UpSta & Num, DnSta & Num=  ,10025.59, 2 ,10041.68, 2 , 0 , 0 , 0 ,,
    4.00    4.00
 -913.61   86.39
    4.00    4.00
 -913.72   86.28
BR Coef=-1 , 0 , 0 ,, 0 ,,,0.8,0,1,0,
WSPro=,,,, 1 ,,,, 0 ,,,, 0 ,,,,-1 ,-1 ,-1 , 0 , 0 , 0 , 0 , 0
BC Design=,, 0 ,, 0 ,,,,,,

Type RM Length L Ch R = 1 ,4670.586,678.386900,678.386900,678.386900
XS GIS Cut Line= 4
869420.923899312755761.716831315869416.358465173755523.391401841
 869350.13366484755336.130145474869193.775543021754953.322578483
#Sta/Elev= 30
9653.176102.11219689.899 101.896 9749.9193.117779769.91491.973169799.91985.92945
9809.92185.888929819.92383.581849829.92583.240359839.92778.745659879.93475.47001
9921.65968.452239942.87366.92765 9953.4863.645699974.69452.7996610017.1252.89022
10059.5562.2253210102.1965.97114   1011368.1098510167.0170.4073310285.8378.17344
10307.4381.2023910329.0480.4395210339.8481.7867910350.6480.4342210361.4481.36574
10372.2480.4604110393.8582.0986110404.65 81.084210447.5582.7890510503.6882.19253
#Mann= 3 , 0 , 0
9653.176    0.04       09653.176    0.04       010503.68    0.04       0
#XS Ineff= 2 , 0
       0                10122.08       0
Bank Sta=9653.176,10503.68
Exp/Cntr=0.3,0.1

Type RM Length L Ch R = 1 ,3992.199,0.000000,0.000000,0.000000
XS GIS Cut Line= 3
870003.027648775755812.892291086869575.595637081754801.606775146
869063.323918036754474.207693614
#Sta/Elev= 30
8830.42260.800598947.55559.447029034.40856.064989210.64755.826289349.24753.65289
9609.80456.233489620.66157.506959642.37455.307179674.94357.085149750.93954.61253
9870.36153.864919892.07454.36853 9902.93 56.63039929.03454.79847 9952.7756.56174
9976.50655.963289996.30448.3787810012.1146.3885310035.8553.2159510089.1553.94224
10107.0556.5539610118.9254.2915610142.6653.7958710356.2856.3070810403.7555.15069
10451.2256.6971810474.9661.9052210498.6970.0272110522.4375.8110910536.28 77.3934
#Mann= 3 , 0 , 0
8830.422    0.04       08830.422    0.04       010536.28    0.04       0
#XS Ineff= 2 , 0
       09918.263        10219.73       0
Bank Sta=8830.422,10536.28
Exp/Cntr=0.3,0.1